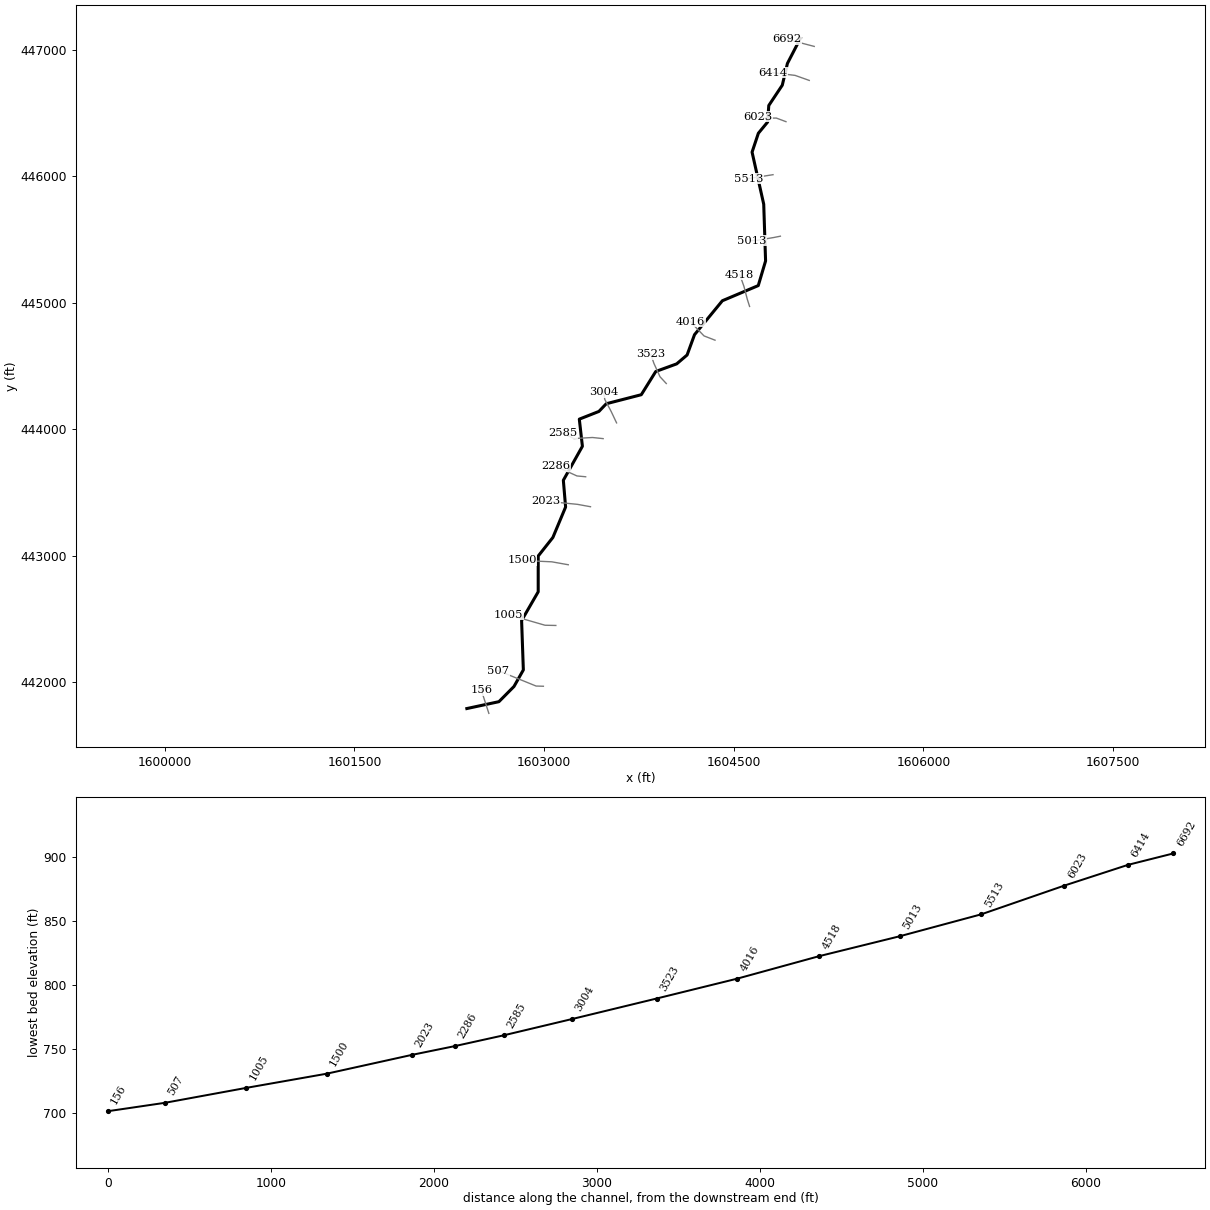
--- LFKPRTRCK.prj (project) ---

Proj Title=LFKPRTRCK
Current Plan=p01
Default Exp/Contr=0,0
English Units
Geom File=g01
Flow File=f01
Plan File=p01
BEGIN DESCRIPTION:
---------- MODELED AS PART OF WVEMD CTP PROGRAM, 2023----------
Stream Name: North Fork Left Fork Proctor Creek
Flood Zone:  AFH
Wetzel County, WV
HEC-RAS Version: RAS 6.3
Vertical Datum: NAVD88
Projection: NAD 1983 StatePlane West Virginia S FIPS 4702 (US Feet)
Terrain: 1-meter West Virginia FEMA R3 South Central (collected 2018-2020)
Land Use: 2019 NLCD
Hydrologic Method:
WV SIR2010-5033 regression equations
Additional Model Notes:
None
END DESCRIPTION:
DSS Export Rating Curves= 0
DSS Export Rating Curve Sorted= 0
DSS Export Volume Flow Curves= 0
DXF OffsetX= 0
DXF OffsetY= 0
DXF ScaleX= 0
DXF ScaleY= 0

--- LFKPRTRCK.p01 (plan) ---

Plan Title=Floodplain
Program Version=6.30
Short Identifier=Floodplain
Geom File=g01
Flow File=f01
Subcritical Flow
K Sum by GR= 0
Std Step Tol= 0.01
Critical Tol= 0.01
Num of Std Step Trials= 20
Max Error Tol= 0.3
Flow Tol Ratio= 0.001
Split Flow NTrial= 30
Split Flow Tol= 0.02
Split Flow Ratio= 0.02
Log Output Level= 0
Friction Slope Method= 1
Unsteady Friction Slope Method= 2
Unsteady Bridges Friction Slope Method= 1
Parabolic Critical Depth
Global Vel Dist= 0 , 0 , 0
Global Log Level= 0
CheckData=False
Encroach Param=-1 ,0,0, 0
Mapping Interval=1HOUR
Computation Time Step Use Courant=        0
Computation Time Step Use Time Series=    0
Computation Time Step Count To Double=0
Computation Time Step Max Doubling=0
Computation Time Step Max Halving=0
Computation Time Step Residence Courant=0
Run HTab= 0
Run UNet= 0
Run Sediment= 0
Run PostProcess= 0
Run WQNet= 0
Run RASMapper=-1
UNET Theta= 0
UNET Theta Warmup= 0
UNET ZTol= 0
UNET ZSATol= 0
UNET MxIter= 0
UNET Max Iter WO Improvement= 0
UNET MaxInSteps= 0
UNET DtIC= 0
UNET DtMin= 0
UNET MaxCRTS= 0
UNET WFStab= 0
UNET SFStab= 0
UNET WFX= 1
UNET SFX= 1
UNET Gravity=32.17405
UNET 1D Methodology=Finite Difference
UNET DSS MLevel= 1
UNET Pardiso=0
UNET DZMax Abort= 0
UNET Use Existing IB Tables= 0
UNET Froude Reduction=False
UNET Froude Limit= 0
UNET Froude Power= 0
UNET D1 Cores= 0
UNET WindReference=Eulerian
UNET WindDragFormulation=Hsu (1988)
UNET D2 Coriolis=0
UNET D2 Cores= 0
UNET D2 Theta= 1
UNET D2 Theta Warmup= 1
UNET D2 Z Tol= 0.01
UNET D2 Volume Tol= 0.01
UNET D2 Max Iterations= 20
UNET D2 Equation= 0
UNET D2 RampUpFraction=0.1
UNET D2 TimeSlices= 1
UNET D2 Turbulence Formulation=Non-Conservative (original)
UNET D2 Eddy Viscosity=0.3
UNET D2 Transverse Eddy Viscosity=0.1
UNET D2 Smagorinsky Mixing=0
UNET D2 BCVolumeCheck=0
UNET D2 Cores=0
UNET D2 SolverType=PARDISO (Direct)
UNET D2 Minimum Iterations= 3
UNET D2 Maximum Iterations= 30
UNET D2 Restart Number= 10
UNET D2 Relaxation Coeff=1.3
UNET D2 SOR Precondition Iterations= 10
UNET D2 ILUT Maximum Fill= 8
UNET D2 ILUT Tolerance=1E-08
UNET D2 Convergence Tolerance=0.00001
UNET D1D2 MaxIter= 0
UNET D1D2 ZTol=0.01
UNET D1D2 QTol=0.1
UNET D1D2 MinQTol=1
Write IC File= 0
Write IC File at Fixed DateTime=0
Write IC File at Sim End=0
Echo Input=False
Echo Parameters=False
Echo Output=False
Write Detailed= 0
HDF Write Warmup=0
HDF Write Time Slices=0
HDF Flush=0
HDF Compression= 1
HDF Chunk Size= 1
HDF Spatial Parts= 1
HDF Use Max Rows=0
HDF Fixed Rows= 1
Calibration Method= 0
Calibration Iterations= 20
Calibration Max Change=0.05
Calibration Tolerance=0.2
Calibration Maximum=1.5
Calibration Minimum=0.5
Calibration Optimization Method= 1
WQ AD Non Conservative
WQ ULTIMATE=-1
WQ Max Comp Step=1HOUR
WQ Output Interval=15MIN
WQ Output Selected Increments= 0
WQ Output face flow=0
WQ Output face velocity=0
WQ Output face area=0
WQ Output face dispersion=0
WQ Output cell volume=0
WQ Output cell surface area=0
WQ Output cell continuity=0
WQ Output cumulative cell continuity=0
WQ Output face conc=0
WQ Output face dconc_dx=0
WQ Output face courant=0
WQ Output face peclet=0
WQ Output face adv mass=0
WQ Output face disp mass=0
WQ Output cell mass=0
WQ Output cell source sink temp=0
WQ Output nsm pathways=0
WQ Output nsm derived pathways=0
WQ Create Restart=0
WQ Fixed Restart=0
WQ System Summary=0
WQ Write To DSS=0
Sorting and Armoring Iterations= 10
XS Update Threshold= 0.02
Bed Roughness Predictor= 0
Hydraulics Update Threshold= 0.02
Energy Slope Method= 1
Volume Change Method= 1
Sediment Retention Method= 0
Sediment TS Multiplier= 1
Warm Up Method= 0
XS Weighting Method= 0
Number of US Weighted Cross Sections= 1
Number of DS Weighted Cross Sections= 1
Upstream XS Weight=0
Main XS Weight=1
Downstream XS Weight=0
Number of DS XS's Weighted with US Boundary= 1
Upstream Boundary Weight= 1
Weight of XSs Associated with US Boundary= 0
Number of US XS's Weighted with DS Boundary= 1
Downstream Boundary Weight= 0.5
Weight of XSs Associated with DS Boundary= 0.5
Percentile Method= 0
Sediment Output Level= 3
Mass or Volume Output= 0
Output Increment Type= 1
Profile and TS Output Increment= 1
Transport Output Increment 1
XS Output Flag= 0
XS Output Increment= 10
Read HDF5 Sediment Hotstart= 0
Sediment Hotstart Type= 0
Write Gradation File= 0
Read Gradation Hotstart= 0
Write HDF5 File= 1
Write Binary Output= 1
Write DSS Sediment File= 0
DSS Sediment Output Type= 1
SV Curve= 0
Specific Gage Flag= 0
Subcell Erosion Methods= 0
Subcell Deposition Methods= 0
Advection Scheme= 1
Matrix Solver= 0
Implicit Weighting Factor= 1
Maximum Outer Loop Convergence Iterations= 5
Convergence Maximum Absolute= 0.001
Convergence RMSE= 0.0001
Grain Fractions Max Abs Error= 0.001
Max Subgrid Regions= 1
Max Subgrid Length Scale= 3.402823E+38
Initial Layer Thickness= 3.402823E+38
Min Layer Thickness= 3.402823E+38
Max Layer Thickness= 3.402823E+38
Number of Layers= 5

--- LFKPRTRCK.f01 (steady flow) ---

Flow Title=Flow
Program Version=6.30
Number of Profiles= 1
Profile Names=F01pct
River Rch & RM=LFKPRTRCK,Main,6692
     740
River Rch & RM=LFKPRTRCK,Main,3004
     849
Boundary for River Rch & Prof#=LFKPRTRCK,Main            , 1
Up Type= 0
Dn Type= 3
Dn Slope=0.01957
DSS Import GetInterval= 0
DSS Import GetPeak= 0
DSS Import FillOption= 0

--- LFKPRTRCK.g01 (geometry) ---

Geom Title=Geometry
Program Version=6.30

River Reach=LFKPRTRCK       ,Main
Reach XY= 30
1605026.74511493447091.5855863431604924.05305382446892.783811577
     1604883.589      446721.071     1604776.727      446560.371
     1604767.754      446429.853     1604694.338      446340.938
     1604644.578      446191.658     1604736.756      445779.711
     1604751.439      445331.056     1604693.522      445136.095
     1604409.646      445016.181     1604189.397      444747.804
     1604130.664      444587.104     1604048.274      444516.951
      1603882.68      444456.586     1603768.477      444273.045
1603491.41401948444201.5970242931603433.26596027444140.824805602
     1603278.219      444079.715     1603302.691      443865.177
     1603151.984       443596.34     1603169.828      443384.759
     1603069.135      443143.862     1602953.148      442997.284
     1602953.148      442714.3251602821.83026636442486.984208404
     1602835.633      442096.399     1602761.499      441965.359
     1602642.466      441845.282      1602388.76       441790.86

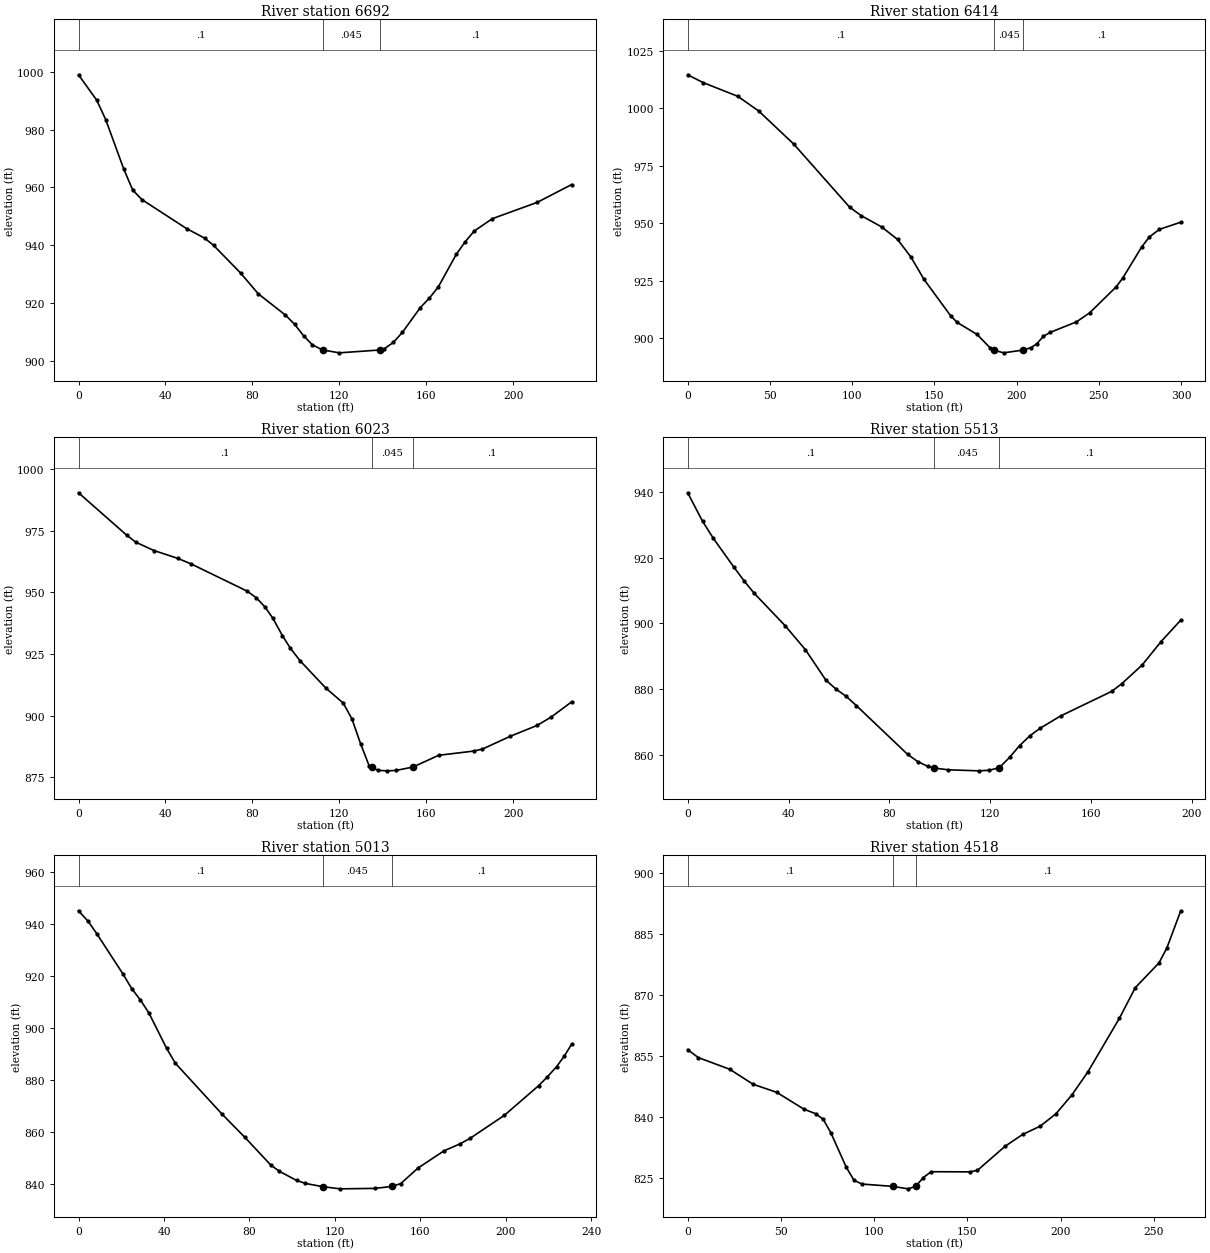
Type RM Length L Ch R = 1 ,6692    ,278.3,278.3,278.3
XS GIS Cut Line= 2
1605136.25420275447027.7312598611604916.82097092447084.937588783
#Sta/Elev= 30
       0  999.04     8.4  990.21    12.5  983.54    20.8   966.4    24.9  959.15
    29.1  955.82    49.7  945.75      58  942.44    62.2  939.89    74.6   930.3
    82.7  923.14    95.2  915.76    99.4  912.58   103.5  908.64   107.6  905.44
   112.3  903.68     120  902.69   138.5  903.67   140.7  904.12   144.8  906.29
     149   909.8   157.2  918.36   161.4  921.66   165.5  925.55   173.8  936.87
   177.8  941.12     182  944.89   190.3  949.16     211  954.83   226.8  960.99
#Mann= 3 ,-1,0
       0      .1       0   112.3    .045       0   138.5      .1       0
Bank Sta=112.3,138.5
XS Rating Curve= 0 ,0
Exp/Cntr(USF)=0,0
Exp/Cntr=0.3,0.1

Type RM Length L Ch R = 1 ,6414    ,390.6,390.6,390.6
XS GIS Cut Line= 3
1605096.84260819446758.7763424871604984.41144951446798.606214846
 1604805.2071359446819.991157615
#Sta/Elev= 30
       0 1014.63     9.3 1011.26    30.5 1005.26    43.2  998.87    64.4  984.57
    98.4  957.13   105.4  953.45   117.9  948.51   127.6  943.05   135.7  935.44
   143.7  925.67   159.9  909.86   163.9  906.95     176  901.74     184  895.83
   186.1  894.95   192.1  893.76   204.1  894.98   208.9  896.08   212.2  897.67
   216.3  900.94   220.3  902.62   236.4  907.23   244.5   911.2   260.6  922.49
   264.6  926.35     276  939.74   280.7  944.13   286.8  947.43   299.8  950.55
#Mann= 3 ,-1,0
       0      .1       0   186.1    .045       0   204.1      .1       0
Bank Sta=186.1,204.1
XS Rating Curve= 0 ,0
Exp/Cntr(USF)=0,0
Exp/Cntr=0.3,0.1

Type RM Length L Ch R = 1 ,6023    ,510,510,510
XS GIS Cut Line= 4
1604912.77270126446432.4914122731604836.69682206446460.923811573
1604734.49387322446460.1553683491604692.99793911446473.218903162
#Sta/Elev= 30
       0   990.5    22.1  973.34    26.3  970.46    34.7  967.05    45.8  963.82
    51.9  961.57    77.6  950.55    81.8  947.87    85.8  944.12    89.5  939.45
    93.8  932.52    97.5  927.35     102  922.24   113.8  911.19   121.8  905.09
   125.8   898.7   129.8  888.59   133.8  879.47   135.1878.9207   137.8  877.78
   141.8  877.56   145.9   877.7   153.8  879.07   165.8  883.88   181.8  885.58
   185.9   886.4   198.5  891.53     211  895.99   217.5   899.4   226.9  905.55
#Mann= 3 ,-1,0
       0      .1       0   135.1    .045       0   153.8      .1       0
Bank Sta=135.1,153.8
XS Rating Curve= 0 ,0
Exp/Cntr(USF)=0,0
Exp/Cntr=0.3,0.1

Type RM Length L Ch R = 1 ,5513    ,500.1,500.1,500.1
XS GIS Cut Line= 2
1604810.23867549446013.1937376031604616.98592132445982.741788461
#Sta/Elev= 30
       0  939.81     5.9  931.13    10.2   925.9    18.3  917.19    22.4  912.95
    26.4  909.18    38.6  899.37    46.7  892.01    54.8  882.75    58.8  880.02
    62.9  877.78    66.9  874.99    87.2  860.15    91.2  857.94    95.3  856.43
    97.9  855.94   103.4  855.41   115.5   855.1   119.6  855.28   123.6  856.05
   127.7  859.22   131.7  862.81   135.8  865.81   139.8  868.07   147.9   871.8
   168.2  879.31   172.2  881.64   180.3  887.36   187.8  894.49   195.6  901.01
#Mann= 3 ,-1,0
       0      .1       0    97.9    .045       0   123.6      .1       0
Bank Sta=97.9,123.6
XS Rating Curve= 0 ,0
Exp/Cntr(USF)=0,0
Exp/Cntr=0.3,0.1

Type RM Length L Ch R = 1 ,5013    ,495,495,495
XS GIS Cut Line= 4
1604868.51895438445526.8018958431604816.46434046445516.390973059
 1604692.8346324445495.5691274921604640.78001848445491.665031448
#Sta/Elev= 30
       0  945.13     4.5  941.07     8.6  936.24    20.8  920.77    24.9  915.12
      29  910.69    32.9  905.79    41.2  892.14    45.3  886.38    67.1  866.81
    77.8  857.84    89.9  847.18      94   844.7   102.1  841.18   106.2  840.04
   114.3  838.79   122.4  837.96   138.6  838.13   146.7  838.89   150.8  840.01
   158.9  846.01   171.1  852.65   178.5  855.29   183.2  857.42   199.2  866.26
   215.3  877.73   219.3  881.07   223.7  885.06   227.3  889.13   230.7   893.7
#Mann= 3 ,-1,0
       0      .1       0   114.3    .045       0   146.7      .1       0
Bank Sta=114.3,146.7
XS Rating Curve= 0 ,0
Exp/Cntr(USF)=0,0
Exp/Cntr=0.3,0.1

Type RM Length L Ch R = 1 ,4518    ,502.4,502.4,502.4
XS GIS Cut Line= 4
1604624.93875282444971.0590441651604606.71963795445028.319119476
1604580.69233099445128.5242512691604546.85683194445223.523921671
#Sta/Elev= 30
       0  856.58     5.7  854.64    22.5  851.78    35.1  848.08    47.7  846.11
    62.4  841.95    68.6  840.85    72.7  839.48    76.8  836.16    85.1  827.66
    89.2   824.5    93.4  823.56   109.9  822.99   118.2  822.38   122.3  822.98
   126.4  825.16   130.6  826.59   151.2  826.55   155.4  826.91   170.3  832.85
   179.7  835.75   189.1  837.78   197.6  840.85   206.1  845.46   214.6  851.06
   231.6  864.31   240.1  871.82   252.8   877.9     257  881.52   264.5  890.72
#Mann= 3 ,-1,0
       0      .1       0   109.9    .045       0   122.3      .1       0
Bank Sta=109.9,122.3
XS Rating Curve= 0 ,0
Exp/Cntr(USF)=0,0
Exp/Cntr=0.3,0.1

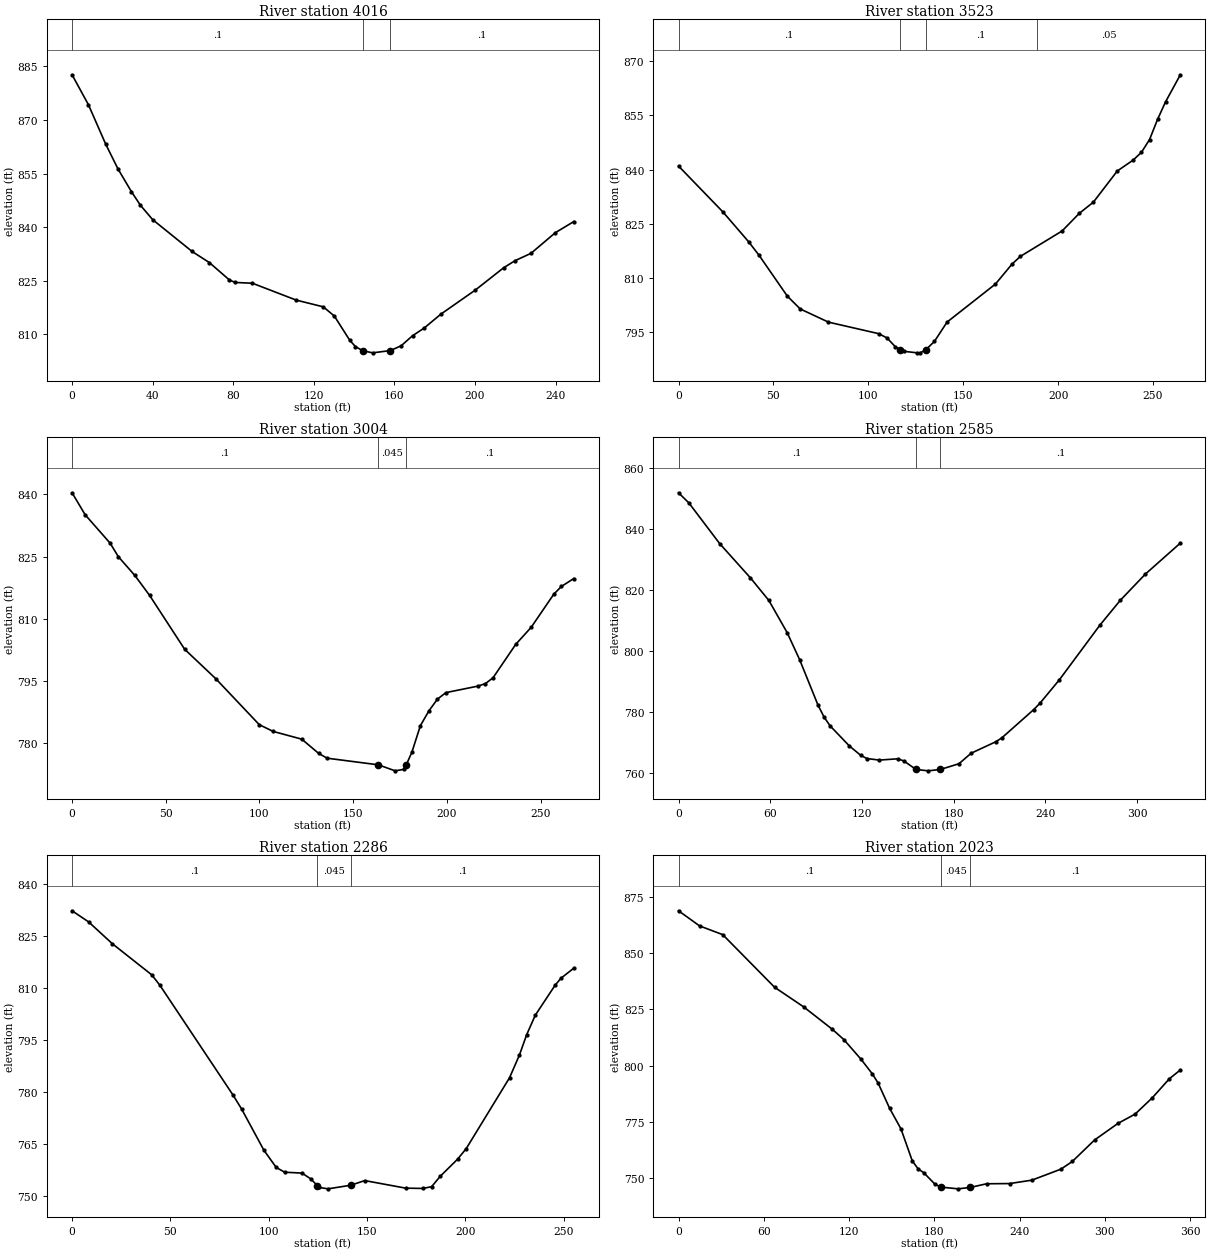
Type RM Length L Ch R = 1 ,4016    ,492.7,492.7,492.7
XS GIS Cut Line= 4
1604351.65202975444704.2791478321604264.46055143444738.114646879
1604196.78955334444808.388375669 1604157.7485929444851.333432152
#Sta/Elev= 30
       0  882.65     8.1  874.29    16.7  863.23    22.8  856.29    29.5   849.9
    33.9  846.15      40   842.1    59.6  833.18    68.2  830.06    78.1  825.21
      81  824.51    89.5   824.3   111.3  819.57   124.7  817.69   130.2  815.11
   137.9  808.28   140.7  806.55   144.3805.4035   149.2  804.81     158  805.44
   163.4   806.8     169  809.59   174.8  811.75   183.2  815.69   200.2  822.39
   214.3  828.65     220  830.64   227.8  832.66   239.9  838.44   249.1  841.57
#Mann= 3 ,-1,0
       0      .1       0   144.3    .045       0     158      .1       0
Bank Sta=144.3,158
XS Rating Curve= 0 ,0
Exp/Cntr(USF)=0,0
Exp/Cntr=0.3,0.1

Type RM Length L Ch R = 1 ,3523    ,518.9,518.9,518.9
XS GIS Cut Line= 4
1603966.11172915444361.4939941191603916.65984593444414.849973385
1603868.50932805444520.2605665711603843.78338644444591.835660709
#Sta/Elev= 30
       0     841    23.4   828.3    36.9  820.08    42.3  816.41    57.3  805.04
    64.1  801.48      79  797.83   105.4  794.65   109.8  793.48   114.2  791.05
   116.7  790.25   118.6  789.77   125.8  789.34   127.4  789.35   130.3   790.2
   134.8  792.48   141.5  797.85     167  808.37   175.7  813.87   180.1  816.01
   202.1  823.04   211.2  827.93   218.6  831.02   231.2  839.64   239.5  842.63
   243.9  844.78   248.2  848.34   252.4   853.9   256.6  858.74   264.4  866.24
#Mann= 4 ,-1,0
       0      .1       0   116.7    .045       0   130.3      .1       0
  188.64     .05       0
Bank Sta=116.7,130.3
XS Rating Curve= 0 ,0
Exp/Cntr(USF)=0,0
Exp/Cntr=0.3,0.1

Type RM Length L Ch R = 1 ,3004    ,419.2,419.2,419.2
XS GIS Cut Line= 4
1603572.89678689444050.2423997151603530.20549665444140.368456889
 1603479.9246437444235.2379907561603469.48899498444295.005797092
#Sta/Elev= 30
       0  840.39       7  835.08    20.3  828.24    24.7  824.97    33.5  820.45
    41.4  815.62    60.1  802.63    76.6  795.58    99.9  784.45   107.3  782.82
   122.6  780.95   131.6  777.52   136.1  776.36   163.5  774.76   172.4  773.31
   176.9  773.66   178.3  774.71   181.4  777.86   185.9  784.22   190.5  787.82
     195  790.61   199.5  792.18   216.5  793.74   220.6  794.35   224.7  795.78
   236.8  803.84     245  807.92   257.1  815.93   261.2  817.81   267.8  819.71
#Mann= 3 ,-1,0
       0      .1       0   163.5    .045       0   178.3      .1       0
Bank Sta=163.5,178.3
XS Rating Curve= 0 ,0
Exp/Cntr(USF)=0,0
Exp/Cntr=0.3,0.1

Type RM Length L Ch R = 1 ,2585    ,299.5,299.5,299.5
XS GIS Cut Line= 4
1603466.84315856443925.7036959971603382.51468401443934.663596417
1603235.36149592443926.3361595561603148.60857773443967.551701491
#Sta/Elev= 30
       0  851.87     6.8  848.52    26.9  835.19      47  823.95    59.1  816.51
    71.1  805.91    79.2  797.09    91.2   782.2    95.2  778.22    99.2  775.32
   111.8  768.73   119.3  765.63   123.2  764.63   131.3  764.12   143.3  764.54
   147.3  763.86   155.3  761.05   163.3  760.59   171.3  761.05   183.4  762.92
   191.4  766.38   207.4  770.11   211.4  771.39   232.2  780.64   236.3  782.73
   249.1  790.48   275.6  808.42   288.9  816.55   305.3  825.16   328.2  835.35
#Mann= 3 ,-1,0
       0      .1       0   155.3    .045       0   171.3      .1       0
Bank Sta=155.3,171.3
XS Rating Curve= 0 ,0
Exp/Cntr(USF)=0,0
Exp/Cntr=0.3,0.1

Type RM Length L Ch R = 1 ,2286    ,262.3,262.3,262.3
XS GIS Cut Line= 3
1603328.48087715443624.0912721351603259.50851371443630.598098875
1603090.33101848443707.378654405
#Sta/Elev= 30
       0  832.31     8.4  829.11    20.5   822.8    40.5  813.85    44.6  810.88
    81.8  779.22    86.2  775.17    97.5  763.32   103.8  758.33   108.1  756.96
   116.9  756.71   121.3  755.06   124.7  753.11   125.7  752.57   130.1  752.17
   141.7  753.21   148.8  754.55   169.6  752.37   178.4  752.28   182.8   752.8
   187.2   755.8     196  760.73   200.4  763.78   222.4  784.19   227.4  790.69
   231.1  796.58   235.5  802.22   245.5   810.8   248.5  812.85   255.1  815.78
#Mann= 3 ,-1,0
       0      .1       0   124.7    .045       0   141.7      .1       0
Bank Sta=124.7,141.7
XS Rating Curve= 0 ,0
Exp/Cntr(USF)=0,0
Exp/Cntr=0.3,0.1

Type RM Length L Ch R = 1 ,2023    ,523.7,523.7,523.7
XS GIS Cut Line= 3
1603366.66893892443387.1698531231603263.60080336443405.909514133
1603016.47152378 443430.50531921
#Sta/Elev= 30
       0  868.85    14.8  862.13    31.1  858.25    67.6  834.87      88  826.19
   108.3  816.17   116.3  811.66   128.4  802.92   136.4  796.37   140.4  792.39
   148.5  781.15   156.5     772   164.5  757.73   168.6  754.21   172.6  752.48
   180.6   747.3     185746.0932   196.7  745.34   205.4  745.98   216.8  747.59
   232.9  747.68   248.6  749.19   269.1  754.09   277.1   757.5   292.8  767.06
   309.2   774.4   321.3  778.54   333.4  785.79   345.4  794.24   353.1  798.14
#Mann= 3 ,-1,0
       0      .1       0     185    .045       0   205.4      .1       0
Bank Sta=185,205.4
XS Rating Curve= 0 ,0
Exp/Cntr(USF)=0,0
Exp/Cntr=0.3,0.1

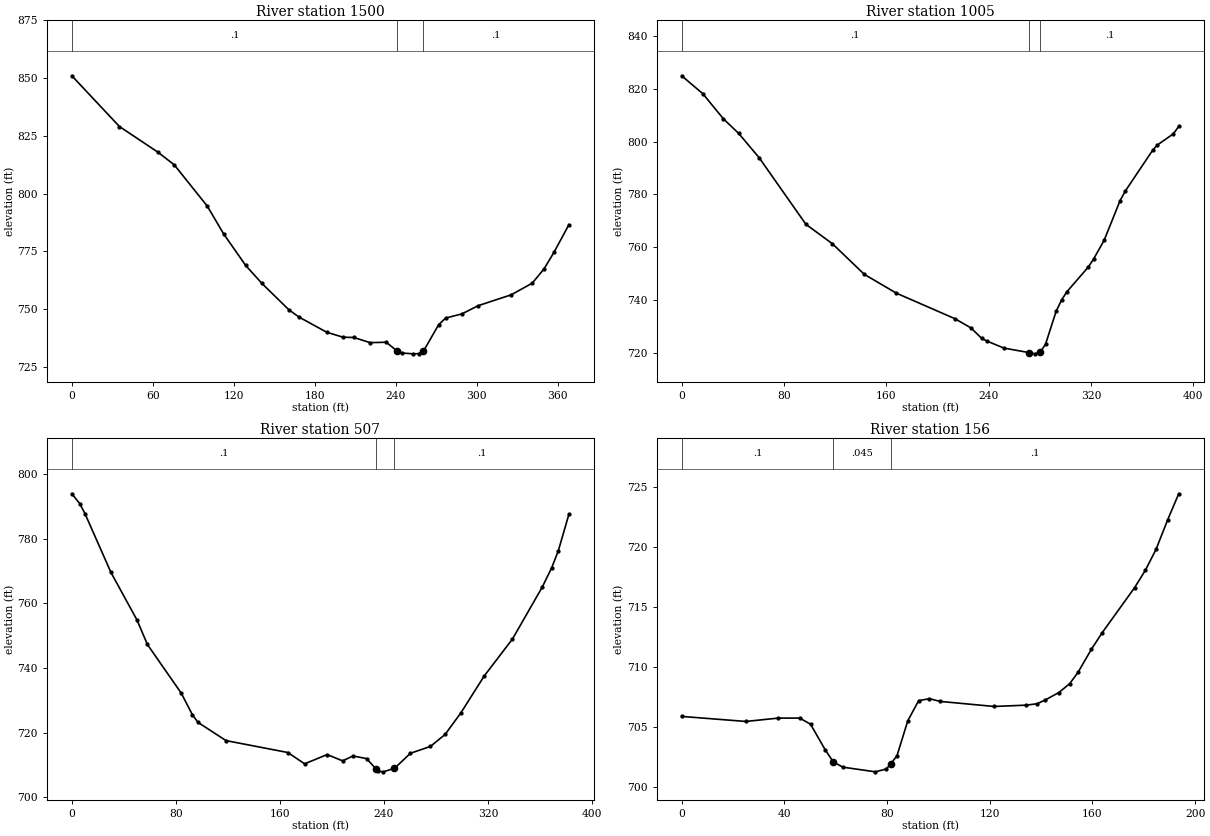
Type RM Length L Ch R = 1 ,1500    ,494.8,494.8,494.8
XS GIS Cut Line= 3
 1603190.8845058442928.2280787781603060.56945723442951.434868248
1602824.93128723442962.145694158
#Sta/Elev= 30
       0  851.02    35.3  829.02    63.8  817.92    75.9  812.43   100.3   794.6
   112.5   782.5   128.8  768.86   140.8   761.1   160.8  749.66   168.3  746.52
   188.9  739.93   200.9  737.81   208.9  737.68   220.9  735.45   232.9  735.62
   240.9  731.83   244.9  730.94   252.9   730.6   256.9  730.69   260.2  731.99
     261   732.3   271.7  743.22     277  746.11     289  747.91     301  751.46
   325.4  756.15     341  761.18   349.8  767.41   357.1  774.51   368.2  786.52
#Mann= 3 ,-1,0
       0      .1       0   240.9    .045       0   260.2      .1       0
Bank Sta=240.9,260.2
XS Rating Curve= 0 ,0
Exp/Cntr(USF)=0,0
Exp/Cntr=0.3,0.1

Type RM Length L Ch R = 1 ,1005    ,498.1,498.1,498.1
XS GIS Cut Line= 3
1603092.70193496442448.0260505171603007.01532769442449.811188168
1602716.03789049 442533.71265779
#Sta/Elev= 30
       0  824.92    16.6   818.1    32.6  808.61    44.6  803.06    60.6  793.84
    97.1  768.62   117.9  761.21   142.8  749.62   167.8  742.51   213.6  732.82
   226.1  729.33   234.4  725.42   238.6  724.35   251.8  721.69   271.2     720
   276.1   719.5   280.2   720.1   284.4  723.14   292.7  735.64   296.9  739.87
     301  742.98   317.7  752.34   321.9  755.39   330.2  762.53   342.7  777.62
   346.8  781.25   368.1  796.67   371.8  798.67   384.3  802.91   388.5  805.72
#Mann= 3 ,-1,0
       0      .1       0   271.2    .045       0   280.2      .1       0
Bank Sta=271.2,280.2
XS Rating Curve= 0 ,0
Exp/Cntr(USF)=0,0
Exp/Cntr=0.3,0.1

Type RM Length L Ch R = 1 ,507     ,350.3,350.3,350.3
XS GIS Cut Line= 3
1602994.21805158441967.3214162351602936.37959167441968.928040121
1602635.94092492442091.031455486
#Sta/Elev= 30
       0  793.86     6.1  790.82    10.1  787.73    30.1  769.51    50.1  754.82
    58.1  747.25    84.1  732.21    92.7  725.51      97  723.14   118.6  717.51
   166.1  713.83     179  710.33   196.3  713.19   208.2  711.26   216.2  712.76
   226.6  711.95   233.6  708.86   235.2  708.12   239.5  707.85   248.1  708.95
   260.4   713.6   275.7   715.7     287  719.41   299.1  726.07   317.2  737.56
   338.8  748.93   361.7  764.99     369  770.99     374  776.15   382.2  787.51
#Mann= 3 ,-1,0
       0      .1       0   233.6    .045       0   248.1      .1       0
Bank Sta=233.6,248.1
XS Rating Curve= 0 ,0
Exp/Cntr(USF)=0,0
Exp/Cntr=0.3,0.1

Type RM Length L Ch R = 1 ,156     ,,,
XS GIS Cut Line= 2
1602562.79715767441752.7514829691602503.12328186441936.941534821
#Sta/Elev= 30
       0  705.91      25  705.49    37.6  705.77      46  705.77    50.2  705.26
    55.9  703.13    59.1  702.11    62.8  701.68    75.5  701.29    79.7  701.53
    81.4  701.94    83.9  702.65    88.1  705.56    92.3  707.22    96.5  707.39
   100.7  707.16   121.7  706.74   134.3  706.85   138.5  706.97   141.7  707.29
   146.9   707.9   151.1  708.63   154.4  709.59   159.6  711.51   163.8  712.89
   176.4  716.64   180.6  718.09   184.8  719.85   189.3   722.3   193.6  724.47
#Mann= 3 ,-1,0
       0      .1       0    59.1    .045       0    81.4      .1       0
Bank Sta=59.1,81.4
XS Rating Curve= 0 ,0
Exp/Cntr(USF)=0,0
Exp/Cntr=0.3,0.1
LCMann Table=0

Chan Stop Cuts=-1
Use User Specified Reach Order=0
Composite Channel Slope=5